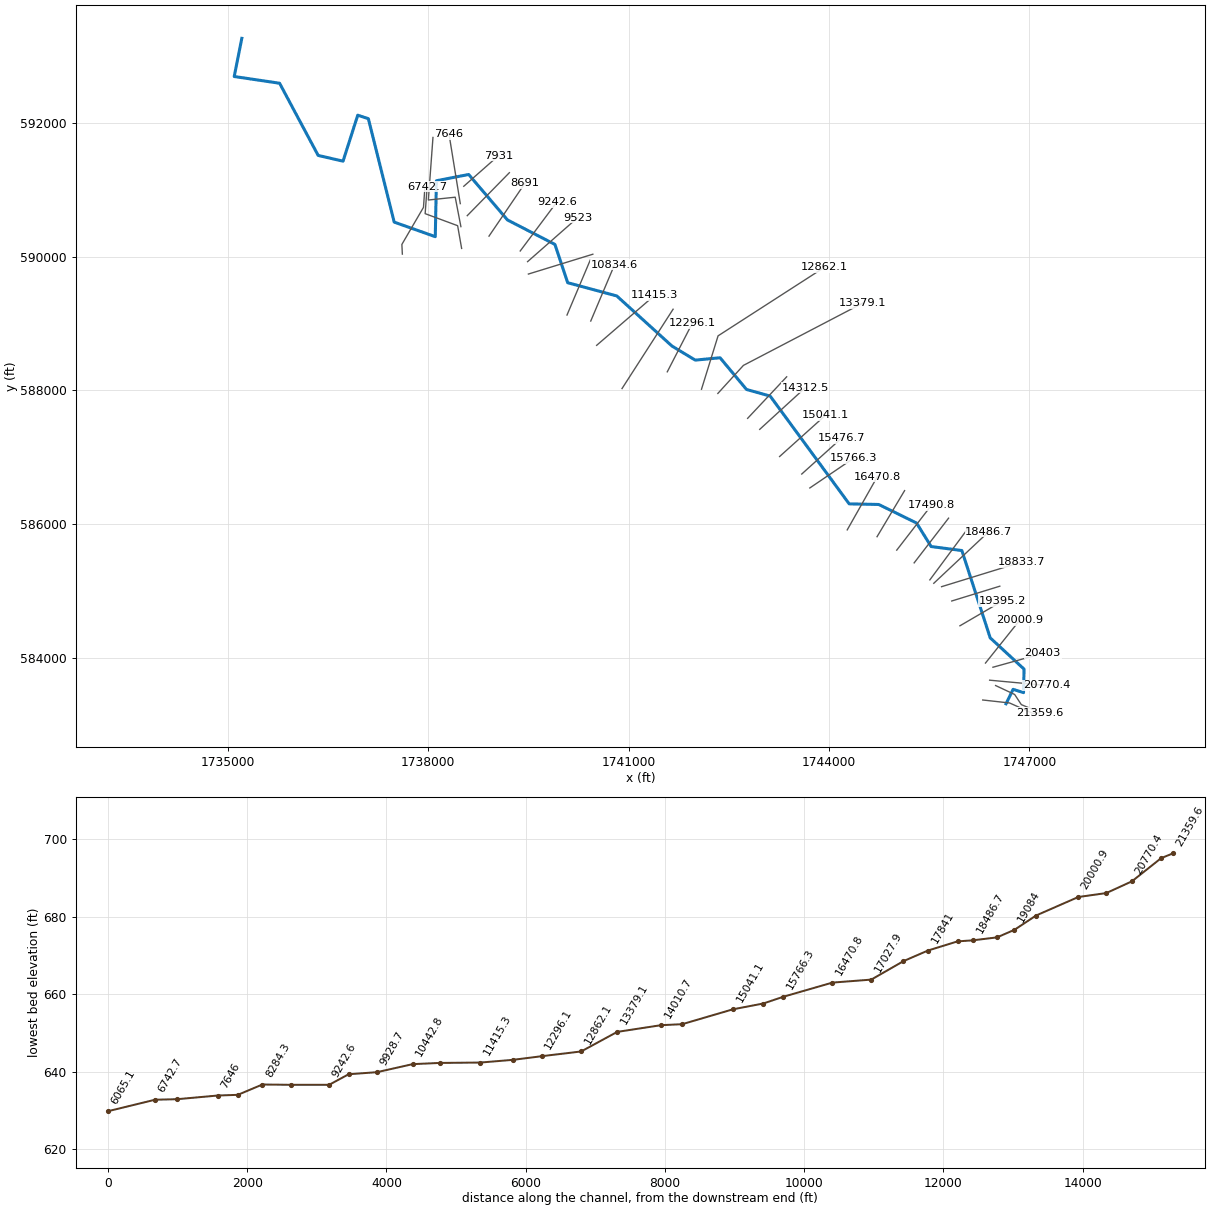
--- CherryFk.prj (project) ---

Proj Title=CherryFk
Current Plan=p01
Default Exp/Contr=0,0
English Units
Geom File=g01
Flow File=f01
Plan File=p01
BEGIN DESCRIPTION:
AMEC Environment & Infrastructure, 2013
Projection: NAD 1983 State Plane West Virginia South FIPS 4702 (US Feet)
Vertical Datum: NAVD 1988
END DESCRIPTION:
DSS Export Rating Curves= 0
DSS Export Rating Curve Sorted= 0
DSS Export Volume Flow Curves= 0
DXF OffsetX= 0
DXF OffsetY= 0
DXF ScaleX= 0
DXF ScaleY= 0

--- CherryFk.p01 (plan) ---

Plan Title=Floodplain
Program Version=4.00
Geom File=g01
Flow File=f01
K Sum by GR=0
Std Step Tol=0.01
Critical Tol=0.01
Num of Std Step Trials=20
Max Error Tol=0.3
Flow Tol Ratio=0.001
Split Flow NTrial=30
Split Flow Tol=0.02
Split Flow Ratio=0.02
Log Output Level=0
Friction Slope Method=1
Unsteady Friction Slope Method=2
Unsteady Bridges Friction Slope Method=1
Global Log Level=0
CheckData=False
Run HTab=0
Run UNet=0
Run PostProcess=0
UNET Theta=0
UNET Theta Warmup=0
UNET ZTol=0
UNET ZSATol=0
UNET MxIter=0
UNET MaxInSteps=0
UNET DtIC=0
UNET DtMin=0
UNET MaxCRTS=0
UNET WFStab=0
UNET SFStab=0
UNET WFX=0
UNET SFX=0
UNET DSS MLevel=0
UNET DZMax Abort=0
UNET Convert EG Bridges=0
UNET Use Existing IB Tables=0
UNET Froude Limit=0
UNET Froude Power=0
Write IC File=0
Echo Input=False
Echo Output=False
Write Detailed=0

--- CherryFk.f01 (steady flow) ---

Flow Title=USGS Regress. Eqn. (2010) - Western-Plateaus
Program Version=4.00
Number of Profiles=1
Profile Names=P100yr
River Rch & RM=CherryFk,Main      ,21359.6
     832
River Rch & RM=CherryFk,Main      ,20403
     899
River Rch & RM=CherryFk,Main      ,19084
     924
River Rch & RM=CherryFk,Main      ,18486.7
     947
River Rch & RM=CherryFk,Main      ,17841
    1461
River Rch & RM=CherryFk,Main      ,17027.9
    1476
River Rch & RM=CherryFk,Main      ,15041.1
    1516
River Rch & RM=CherryFk,Main      ,13379.1
    1575
River Rch & RM=CherryFk,Main      ,12862.1
    2745
River Rch & RM=CherryFk,Main      ,11415.3
    2764
River Rch & RM=CherryFk,Main      ,10834.6
    3048
River Rch & RM=CherryFk,Main      ,9523
    3088
River Rch & RM=CherryFk,Main      ,5381.8
    3149
River Rch & RM=CherryFk,Main      ,3482.3
    3180
River Rch & RM=CherryFk,Main      ,2570.2
    3291
River Rch & RM=CherryFk,Main      ,34.6
    3319
Boundary for River Rch & Prof#=CherryFk,Main      ,1
Up Type=0
Dn Type=3
Dn Slope=0.001733

--- CherryFk.g01 (geometry) ---

Geom Title=USGS 3m DEM
Program Version=4.10

River Reach=CherryFk        ,Main
Reach XY= 30
     1746649.682      583312.349     1746755.035      583528.448
     1746911.167      583479.157     1746919.268      583830.667
     1746412.758      584298.115     1745988.279      585604.104
     1745528.643         585664.     1745310.371      586015.485
     1744744.789      586292.906     1744302.081      586302.021
     1743119.789         587914.     1742765.623      588012.958
     1742369.789      588486.917     1741998.695       588451.76
     1741649.737      588662.698     1740824.216      589411.396
     1740089.841      589609.312     1739898.435      590182.229
     1739188.765      590547.737      1738608.07      591227.802
     1738124.998      591134.052      1738108.07      590298.115
     1737493.487      590515.562     1737106.768      592062.437
     1736947.914      592114.521     1736727.862      591427.021
     1736355.466      591512.958     1735778.209      592592.385
      1735099.39       592693.08     1735212.757      593263.989

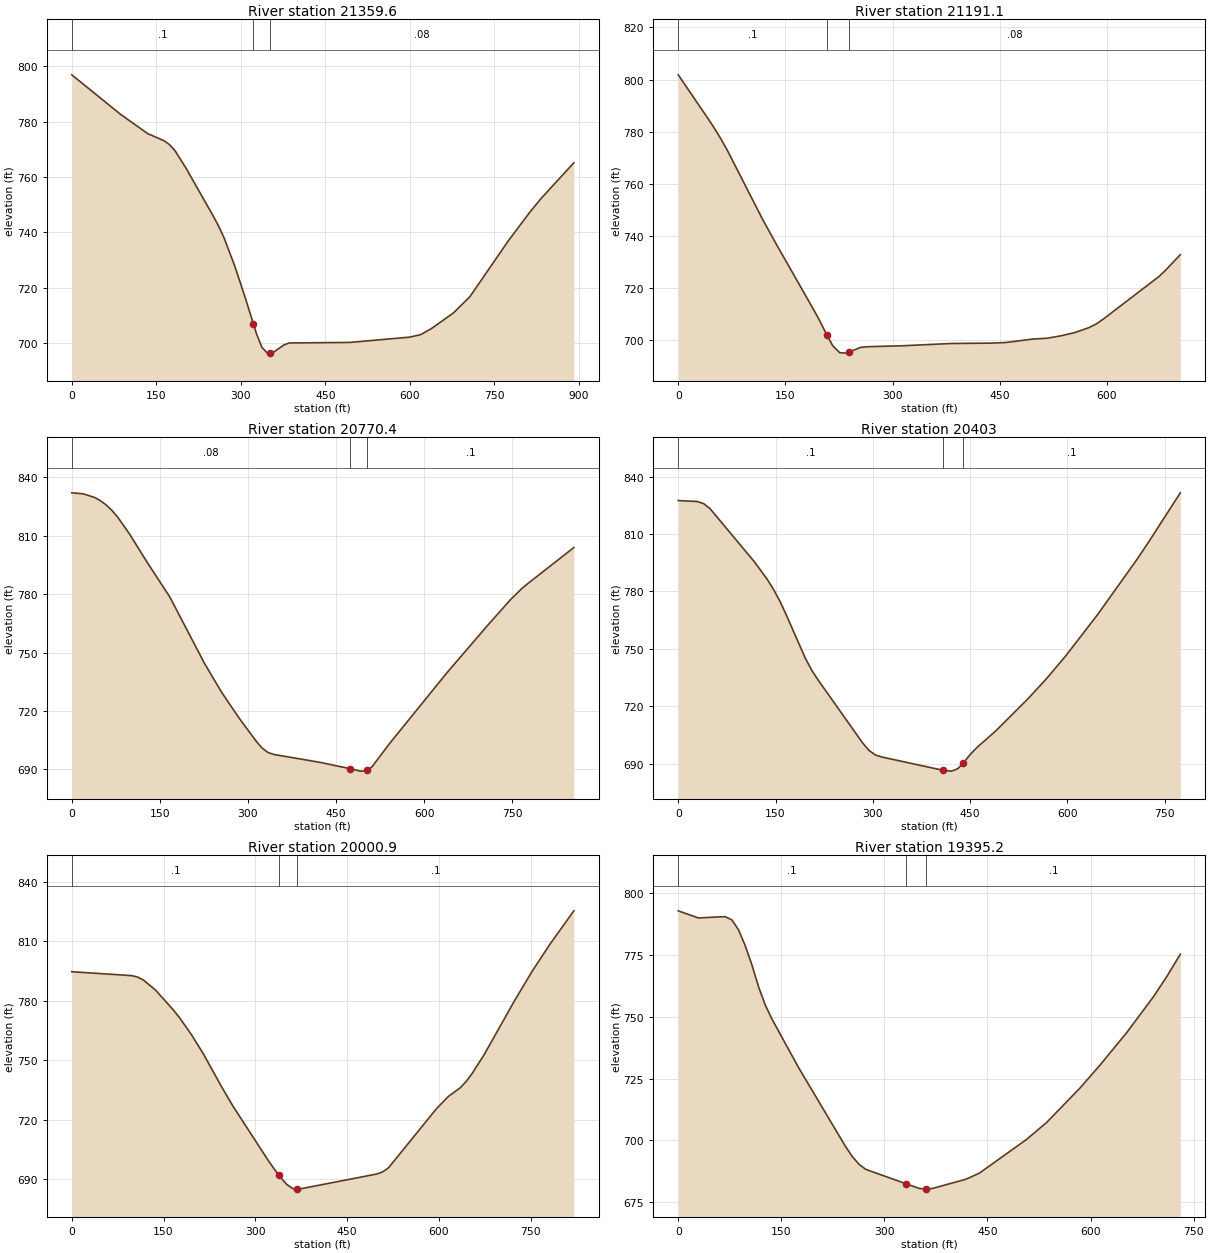
Type RM Length L Ch R = 1 ,21359.6 ,180.7,168.5,158.8
XS GIS Cut Line= 4
     1746300.495      583369.051     1746703.007      583324.381
     1747049.157      583168.908     1747155.367      583176.292
#Sta/Elev= 30
       0  796.96    86.8  782.64     135  775.68   163.9  773.12   173.6   771.7
   183.2  769.53   202.5   763.3   250.7  746.03   260.4  742.34     270  738.15
   289.3   727.8   308.6  715.88   322.3  706.93   327.8  703.33   337.5  698.42
   347.1  696.34   352.4696.4384   356.8  696.52   376.1  699.26   385.7  700.02
   492.6   700.2   599.6  702.12     619  703.02   638.5  705.26   677.4   710.9
   706.6  716.79   774.7  736.97   813.5  747.48   832.8  752.26   890.9  765.16
#Mann= 3 , 0 , 0
       0      .1       0   322.3    .045       0   352.4     .08       0
Bank Sta=322.3,352.4
XS Rating Curve= 0 ,0
Exp/Cntr=0.3,0.1

Type RM Length L Ch R = 1 ,21191.1 ,410.1,420.8,434.4
XS GIS Cut Line= 4
     1746493.624      583585.065     1746778.323      583451.755
     1746878.312      583299.743     1747068.818      583220.568
#Sta/Elev= 30
       0  801.83    39.3  786.02    49.1  781.99    58.9  777.65    68.8  772.84
   117.9   746.5   137.5  736.77   186.6  713.18   196.5   708.3   208.1  702.04
   216.1  697.99     226  695.28   235.8  695.12   238.4695.4357   255.4  697.34
   265.2  697.58   314.4  697.95   381.4  698.81   438.9  698.97     458  699.18
   496.3  700.52     516  700.82   535.6  701.76   555.3  703.02   574.9  704.92
   584.7  706.26   594.6  708.12   673.2   724.6     683  727.19   702.6  732.88
#Mann= 3 , 0 , 0
       0      .1       0   208.1    .045       0   238.4     .08       0
Bank Sta=208.1,238.4
XS Rating Curve= 0 ,0
Exp/Cntr=0.3,0.1

Type RM Length L Ch R = 1 ,20770.4 ,353.7,367.3,380.7
XS GIS Cut Line= 2
     1746404.051      583665.328     1747255.493       583586.69
#Sta/Elev= 30
       0  832.07    19.7  831.55    39.3  829.65    49.1  827.99      59  825.75
    68.8  822.89    78.6  819.42    98.3  810.98   127.8  796.68   167.1  778.51
     226  744.49   255.5  729.49     285  716.36   314.5  704.36   324.3  700.93
   334.2   698.7     344  697.69   422.6  693.64   473.3  690.42   491.4  689.12
   501.2  689.23   503.6689.7124   511.1  691.22   540.6  703.05   638.8  739.59
   707.6  763.76     747  777.14   766.6  782.94   776.4  785.38   855.1  803.96
#Mann= 3 , 0 , 0
       0     .08       0   473.3    .045       0   503.6      .1       0
Bank Sta=473.3,503.6
XS Rating Curve= 0 ,0
Exp/Cntr=0.3,0.1

Type RM Length L Ch R = 1 ,20403   ,378.2,402.2,426.1
XS GIS Cut Line= 2
      1746453.35      583858.832     1747199.315      584065.804
#Sta/Elev= 30
       0  827.54    29.4  827.04    39.2  825.93      49  823.33   117.6  795.46
   137.2  786.36     147  781.04   156.8  774.92   166.6  767.75     196  745.09
   205.8  738.87   215.6  733.76   284.2  700.89     294  696.96   303.8  694.57
   313.6   693.5   408.9  686.49   421.4   686.1   431.2   687.4   438.9690.1264
   450.8  695.06   460.6  698.46     490  707.26     539  723.84   568.4  734.66
   597.8  746.51   646.8  768.03   705.6  795.96   725.2  805.82   774.1  831.58
#Mann= 3 , 0 , 0
       0      .1       0   408.9    .045       0   438.9      .1       0
Bank Sta=408.9,438.9
XS Rating Curve= 0 ,0
Exp/Cntr=0.3,0.1

Type RM Length L Ch R = 1 ,20000.9 ,619.3,605.7,591.7
XS GIS Cut Line= 2
     1746341.973      583921.629     1746854.492      584562.648
#Sta/Elev= 30
       0  794.64    97.7  792.67   107.5  791.98   117.2  790.42   136.8  785.44
   166.1  775.34   175.9  771.59   195.4  763.04     215  753.31   244.3     737
   263.8  726.74   322.4  698.95   338.3  692.08   351.7  687.33   361.5  685.35
   368.3685.1627   371.3  685.08   498.3  692.68   508.1  693.74   517.8  695.85
     596  725.56   615.5  731.76   635.1  736.18   644.8  739.36   654.6  743.41
   674.2   752.9     723  779.61   752.3  794.73   781.6  808.49   820.7  825.32
#Mann= 3 , 0 , 0
       0      .1       0   338.3    .045       0   368.3      .1       0
Bank Sta=338.3,368.3
XS Rating Curve= 0 ,0
Exp/Cntr=0.3,0.1

Type RM Length L Ch R = 1 ,19395.2 ,319.8,311.2,302.5
XS GIS Cut Line= 2
     1745959.686      584478.685     1746590.849      584846.615
#Sta/Elev= 30
       0  792.98    29.2   790.1    68.2  790.63    77.9  789.34    87.7  785.31
    97.4  778.92   107.2  771.13   116.9  762.21   126.6  754.87   136.4  749.16
   175.3  729.43   243.5  697.54   253.3   693.5     263  690.39   272.8  688.32
   330.9  682.55   350.7   680.6   360.4  680.31   360.9680.3253   370.2  680.61
   418.9  684.33   438.3   686.8   506.5  700.36   535.8  707.22   584.5   721.2
   613.7  730.51   652.6  743.68   691.6  758.23   711.1  766.44   730.6  775.43
#Mann= 3 , 0 , 0
       0      .1       0   330.9    .045       0   360.9      .1       0
Bank Sta=330.9,360.9
XS Rating Curve= 0 ,0
Exp/Cntr=0.3,0.1

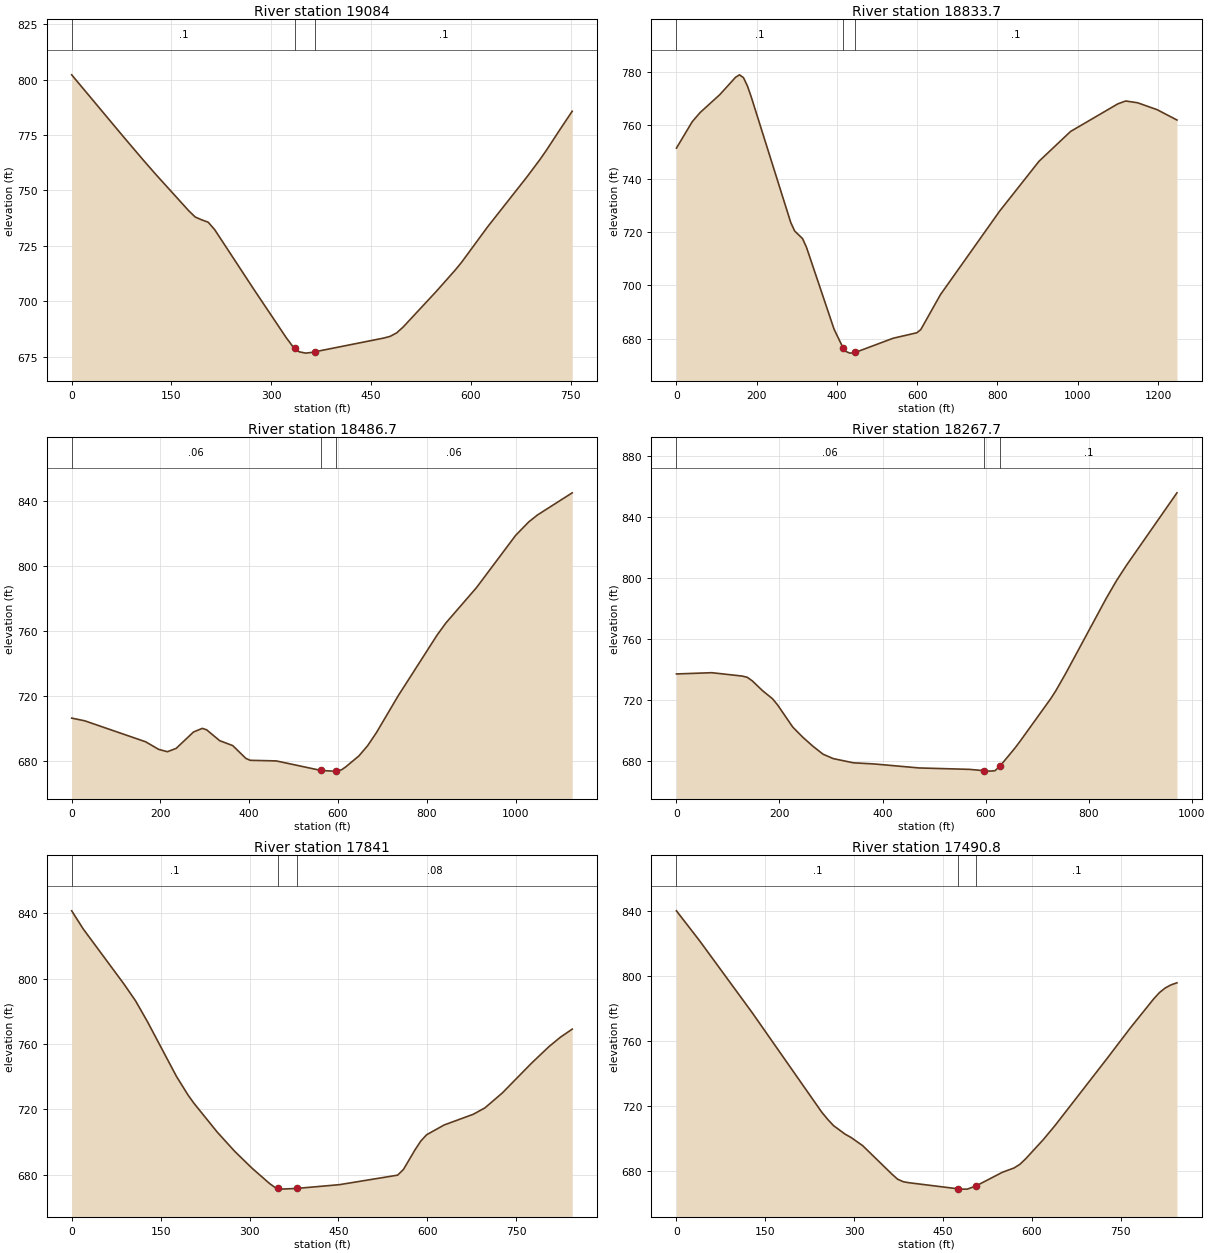
Type RM Length L Ch R = 1 ,19084   ,250.4,250.3,250.4
XS GIS Cut Line= 2
     1745836.971      584849.519     1746556.157      585070.868
#Sta/Elev= 30
       0  802.17    78.2   774.1   107.5  763.76     127  757.07   175.9  740.87
   185.7  738.02   195.4  736.75   205.2  735.68     215  732.32   273.6  705.51
   322.5  683.61   332.3  679.66   335.9  678.75     342  677.21   351.8  676.61
   361.6  676.96   365.9677.2321   469.1   683.4   478.8  684.18   488.6  685.75
   498.4   688.4   547.3  704.18   576.6  714.08   586.4  717.68   625.4  733.62
   684.1  755.98   703.6  763.79   713.4     768   732.9  776.94   752.5  785.75
#Mann= 3 , 0 , 0
       0      .1       0   335.9    .045       0   365.9      .1       0
Bank Sta=335.9,365.9
XS Rating Curve= 0 ,0
Exp/Cntr=0.3,0.1

Type RM Length L Ch R = 1 ,18833.7 ,321.7,346.9,373.2
XS GIS Cut Line= 2
     1745684.806      585063.549     1746876.899      585430.449
#Sta/Elev= 30
       0  751.38    39.3  761.25    58.9  764.67     108  771.38   147.3  777.88
   157.1   778.8     167  777.76   176.8  774.68   186.6  770.45   284.8  723.58
   294.6  720.36   314.3  717.51   324.1  714.26   392.8  683.62   415.3  676.61
   422.3  675.28   432.1  674.66   445.4674.9061   540.2  680.24   599.1  682.28
   608.9  683.46     658  696.57   805.3  727.78   903.5  746.45   982.1   757.6
    1100  767.94  1119.6  769.01  1149.1  768.35  1198.2  765.74  1247.3  761.89
#Mann= 3 , 0 , 0
       0      .1       0   415.3    .045       0   445.4      .1       0
Bank Sta=415.3,445.4
XS Rating Curve= 0 ,0
Exp/Cntr=0.3,0.1

Type RM Length L Ch R = 1 ,18486.7 ,220.3,219,216.3
XS GIS Cut Line= 2
     1745568.096      585114.306     1746390.315      585885.925
#Sta/Elev= 30
       0  706.55    29.4  704.89   166.7  691.96   196.1  687.28   215.7  685.86
   235.3   687.9   274.5  698.01   294.2  700.23     304  699.35   333.4  692.66
   362.8  689.63   392.2  681.79     402  680.56   460.8  680.19   561.5  674.33
   588.3   673.9   595.2673.9282   607.9   674.7   617.7  676.58   647.1  683.28
   666.7  689.56   686.4  697.56   735.4  720.23   823.6  757.85   843.2   765.2
   911.9   786.9  1000.1  819.07  1029.5  827.33  1049.1  831.61  1127.6   845.3
#Mann= 3 , 0 , 0
       0     .06       0   561.5    .045       0   595.2     .06       0
Bank Sta=561.5,595.2
XS Rating Curve= 0 ,0
Exp/Cntr=0.3,0.1

Type RM Length L Ch R = 1 ,18267.7 ,427,426.7,428
XS GIS Cut Line= 2
     1745509.466      585165.296     1746087.894      585945.875
#Sta/Elev= 30
       0   737.3    68.7  738.12   127.6  735.92   137.4  735.12   147.2  732.78
   166.8  726.45   186.5  721.04   196.3  717.02   225.7  702.52   245.3  695.82
     265  689.92   284.6  684.72   304.2  681.85   343.5  679.07   382.7  678.36
     471  675.71   569.2  674.78     597  673.91   608.4  673.63   618.2  673.89
   627.5676.7176   657.5  688.92   667.3  693.34   726.2  720.98     736  726.08
   755.6  737.66   834.2  786.83   853.8  798.24   873.4  808.44   971.5  855.98
#Mann= 3 , 0 , 0
       0     .06       0     597    .045       0   627.5      .1       0
Bank Sta=597,627.5
XS Rating Curve= 0 ,0
Exp/Cntr=0.3,0.1

Type RM Length L Ch R = 1 ,17841   ,351.9,350.2,346.3
XS GIS Cut Line= 2
     1745274.437      585419.679     1745789.576      586088.565
#Sta/Elev= 30
       0  841.55    19.6  830.39    88.4  796.65     108  786.32   127.6  773.87
   176.7  740.27   196.3  728.82   206.2  723.82   245.4  706.21   274.9  694.42
   304.3  684.05   333.8  674.69   343.6  672.14     348  671.74   353.4  671.26
   379.6671.6867   451.6  673.99   549.8  679.81   559.6  683.29   579.2  695.34
     589  700.72   598.8  704.54   628.3  710.52   677.4  717.06     697  720.96
   726.5  730.14   775.5  748.26     805  758.43   824.6  764.28   844.3  769.16
#Mann= 3 , 0 , 0
       0      .1       0     348    .045       0   379.6     .08       0
Bank Sta=348,379.6
XS Rating Curve= 0 ,0
Exp/Cntr=0.3,0.1

Type RM Length L Ch R = 1 ,17490.8 ,458.5,462.9,467.3
XS GIS Cut Line= 2
       1745014.1      585610.409     1745530.759      586278.549
#Sta/Elev= 30
       0  840.12    39.3  821.56   127.7  777.39   245.5  715.84   255.3  711.52
   265.2  707.64   284.8  702.39   294.6  700.39   314.3  695.32   363.4  677.87
   373.2  674.65     383  673.06   392.8  672.46   475.9  668.69   481.2  668.53
     491  668.54   506.1670.6033     550  678.91   569.6  681.56   579.4  683.78
   589.3  687.23   618.7  698.92   638.4  707.54   726.8  749.14     766  767.95
   805.3  785.82   815.1  789.72     825   792.6   834.8  794.51   844.6  795.74
#Mann= 3 , 0 , 0
       0      .1       0   475.9    .045       0   506.1      .1       0
Bank Sta=475.9,506.1
XS Rating Curve= 0 ,0
Exp/Cntr=0.3,0.1

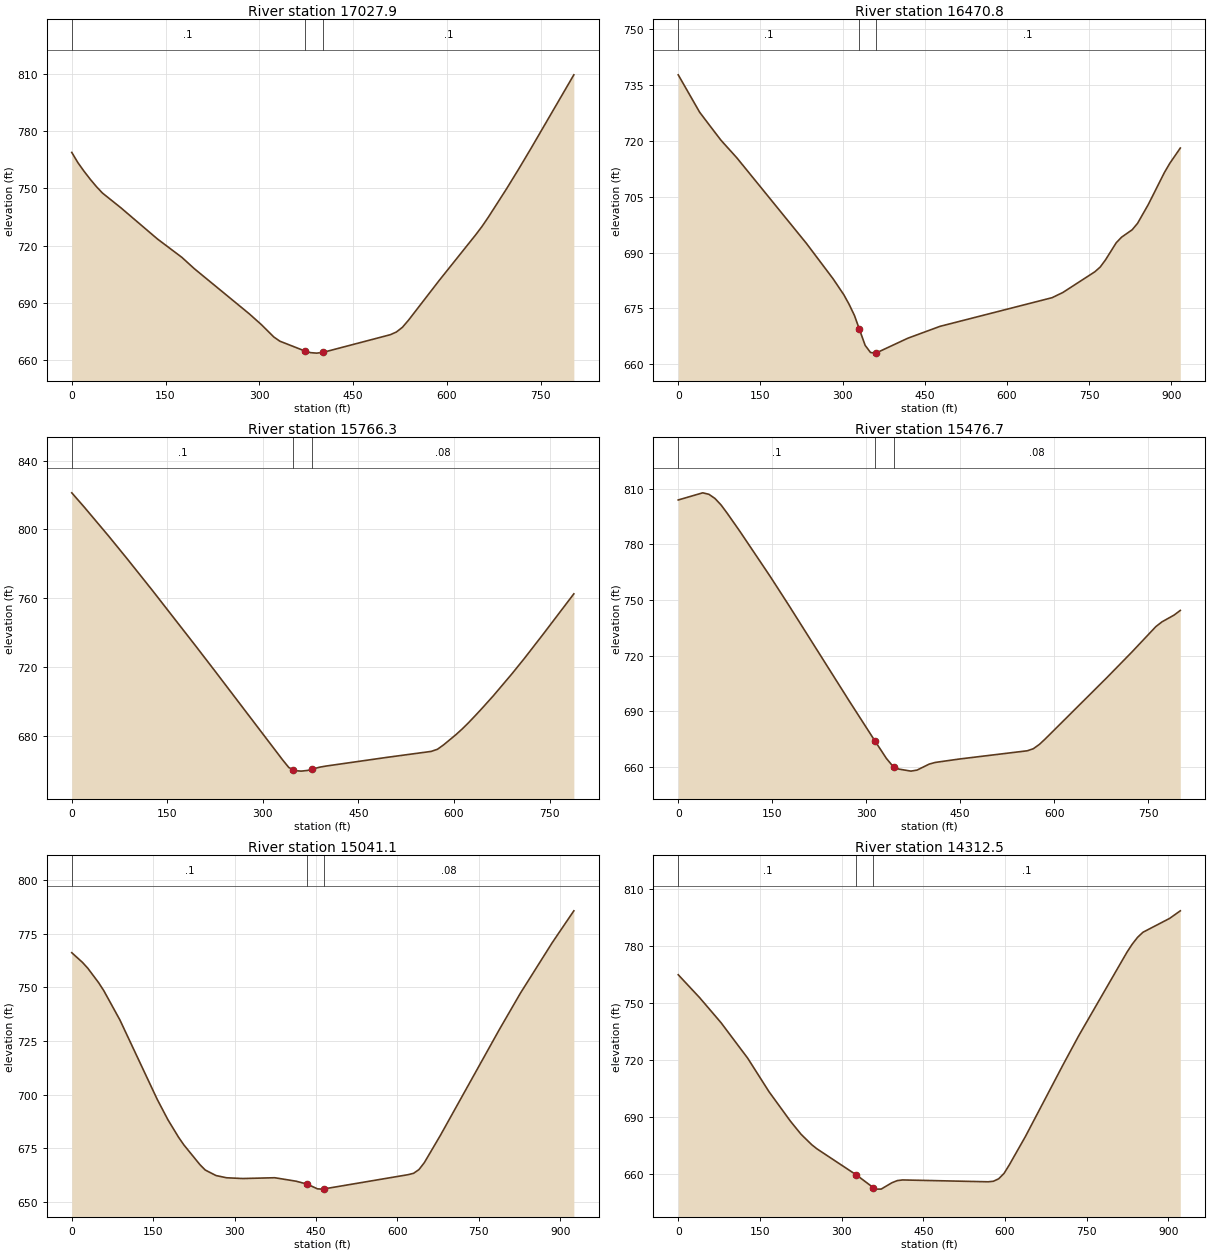
Type RM Length L Ch R = 1 ,17027.9 ,552.9,557.1,560.2
XS GIS Cut Line= 2
     1744719.175      585810.941     1745131.273      586500.263
#Sta/Elev= 30
       0   768.8     9.8  763.44    19.6  758.95    29.4   754.8    39.2  750.98
      49  747.56    78.4  739.86   137.1  723.48   176.3  713.83   195.9  707.98
     284  684.31   303.6  678.58   323.2   672.2     333  669.99   372.4  664.94
     382  664.01   391.8  663.76   402.4664.1961   509.3  673.38   519.1  674.78
   528.9  677.27   538.7  681.02   587.6  701.74   646.4   725.8   656.2  730.05
     666  734.74   695.4  749.72     715  760.16   734.6  770.92   803.1   809.4
#Mann= 3 , 0 , 0
       0      .1       0   372.4    .045       0   402.4      .1       0
Bank Sta=372.4,402.4
XS Rating Curve= 0 ,0
Exp/Cntr=0.3,0.1

Type RM Length L Ch R = 1 ,16470.8 ,721.2,704.5,687.4
XS GIS Cut Line= 2
     1744273.111      585913.121     1744724.589      586710.943
#Sta/Elev= 30
       0  737.73      39  727.71    58.5  723.92      78  720.17   107.3  715.39
     234  692.47   282.8  682.94   302.3  678.68   312.1  676.07   321.8  673.08
   330.5  669.51   341.3  665.07   351.1  663.16   360.8  662.99   360.9662.9963
   419.3     667   477.9  670.18   682.6  677.88   702.2  679.27   760.7  684.84
   770.4   686.1   780.2  688.05   799.7  692.63   809.4  694.12   828.9  696.13
   838.7  697.86   858.2  702.89   887.4  711.42   897.2   713.9   916.7  718.07
#Mann= 3 , 0 , 0
       0      .1       0   330.5    .045       0   360.9      .1       0
Bank Sta=330.5,360.9
XS Rating Curve= 0 ,0
Exp/Cntr=0.3,0.1

Type RM Length L Ch R = 1 ,15766.3 ,284.8,289.6,294.2
XS GIS Cut Line= 2
     1743713.247      586539.952     1744365.379      586982.281
#Sta/Elev= 30
       0  821.26    19.5     813    58.4  795.87    87.6  782.58   126.5   764.5
   194.6  732.11   223.8  718.04   330.8  665.94   340.5   661.5   347.6  660.13
   350.2  659.63     360  659.34   369.7  659.72   377.6660.4855   389.1  661.64
   398.9  662.28   496.1  667.42   564.2  670.82     574  672.07   583.7  674.65
   603.2  680.64   612.9  683.91   622.6  687.46   632.3  691.24   642.1  695.13
   661.5  703.11   690.7   715.9   710.2  724.84   739.4   738.8     788  762.49
#Mann= 3 , 0 , 0
       0      .1       0   347.6    .045       0   377.6     .08       0
Bank Sta=347.6,377.6
XS Rating Curve= 0 ,0
Exp/Cntr=0.3,0.1

Type RM Length L Ch R = 1 ,15476.7 ,435.7,435.6,435.3
XS GIS Cut Line= 2
     1743592.345       586748.09     1744187.378      587284.648
#Sta/Elev= 30
       0  803.95    39.1  807.81    48.9  807.02    58.6  804.77    68.4  801.24
    78.2  796.77    97.7  787.36   146.6  762.76   175.9  747.41   273.6  695.07
   313.9  673.89   332.2  664.44     342  660.44     344 660.087   351.8  658.71
   371.3  657.59   381.1  658.15   400.6   661.4   410.4   662.3   449.5  664.16
     557  668.57   566.7  669.69   576.5  672.07   586.3  675.18     684  708.06
   723.1  721.58   762.1  735.57   771.9  738.16   791.4  741.85   801.2  744.34
#Mann= 3 , 0 , 0
       0      .1       0   313.9    .045       0     344     .08       0
Bank Sta=313.9,344
XS Rating Curve= 0 ,0
Exp/Cntr=0.3,0.1

Type RM Length L Ch R = 1 ,15041.1 ,718.8,728.6,727.5
XS GIS Cut Line= 2
     1743260.916      587009.998     1743948.714      587628.344
#Sta/Elev= 30
       0  766.11    19.7  761.61    29.5  758.89    49.2  752.26      59  748.45
    88.6  734.85   157.4  697.88   177.1  688.39   196.8  680.21   206.6  676.64
   236.1  667.47     246  664.96   265.7  662.41   285.3  661.37   314.9  661.02
   373.9  661.39   413.2  659.78   433.8   658.4   452.6  656.22   462.4  656.09
   463.8656.1579   619.9  662.83   629.7  663.46   639.6  665.19   649.4  668.39
   678.9  681.04   787.1   730.1   826.5  747.29   885.5  770.94   924.9   785.6
#Mann= 3 , 0 , 0
       0      .1       0   433.8    .045       0   463.8     .08       0
Bank Sta=433.8,463.8
XS Rating Curve= 0 ,0
Exp/Cntr=0.3,0.1

Type RM Length L Ch R = 1 ,14312.5 ,300.4,301.8,303
XS GIS Cut Line= 2
     1742963.436      587416.306     1743644.229      588038.079
#Sta/Elev= 30
       0  765.03    39.2  753.01    78.5  739.84   127.5  721.16   166.7  703.51
     206  688.01   225.6   681.1   245.2  675.61     255  673.39   327.1  659.73
   357.9 653.102   362.9  652.25   372.7  652.28   392.3  655.59   402.2  656.73
     412  657.08   568.9  656.11   578.7  656.38   588.5   657.7   598.3  660.52
   608.1  665.08   637.6  679.95   706.2  717.41   735.6  733.03   823.9  776.82
   833.7  781.13   843.5  784.71   853.3  787.37   902.4  794.68     922  798.66
#Mann= 3 , 0 , 0
       0      .1       0   327.1    .045       0   357.9      .1       0
Bank Sta=327.1,357.9
XS Rating Curve= 0 ,0
Exp/Cntr=0.3,0.1

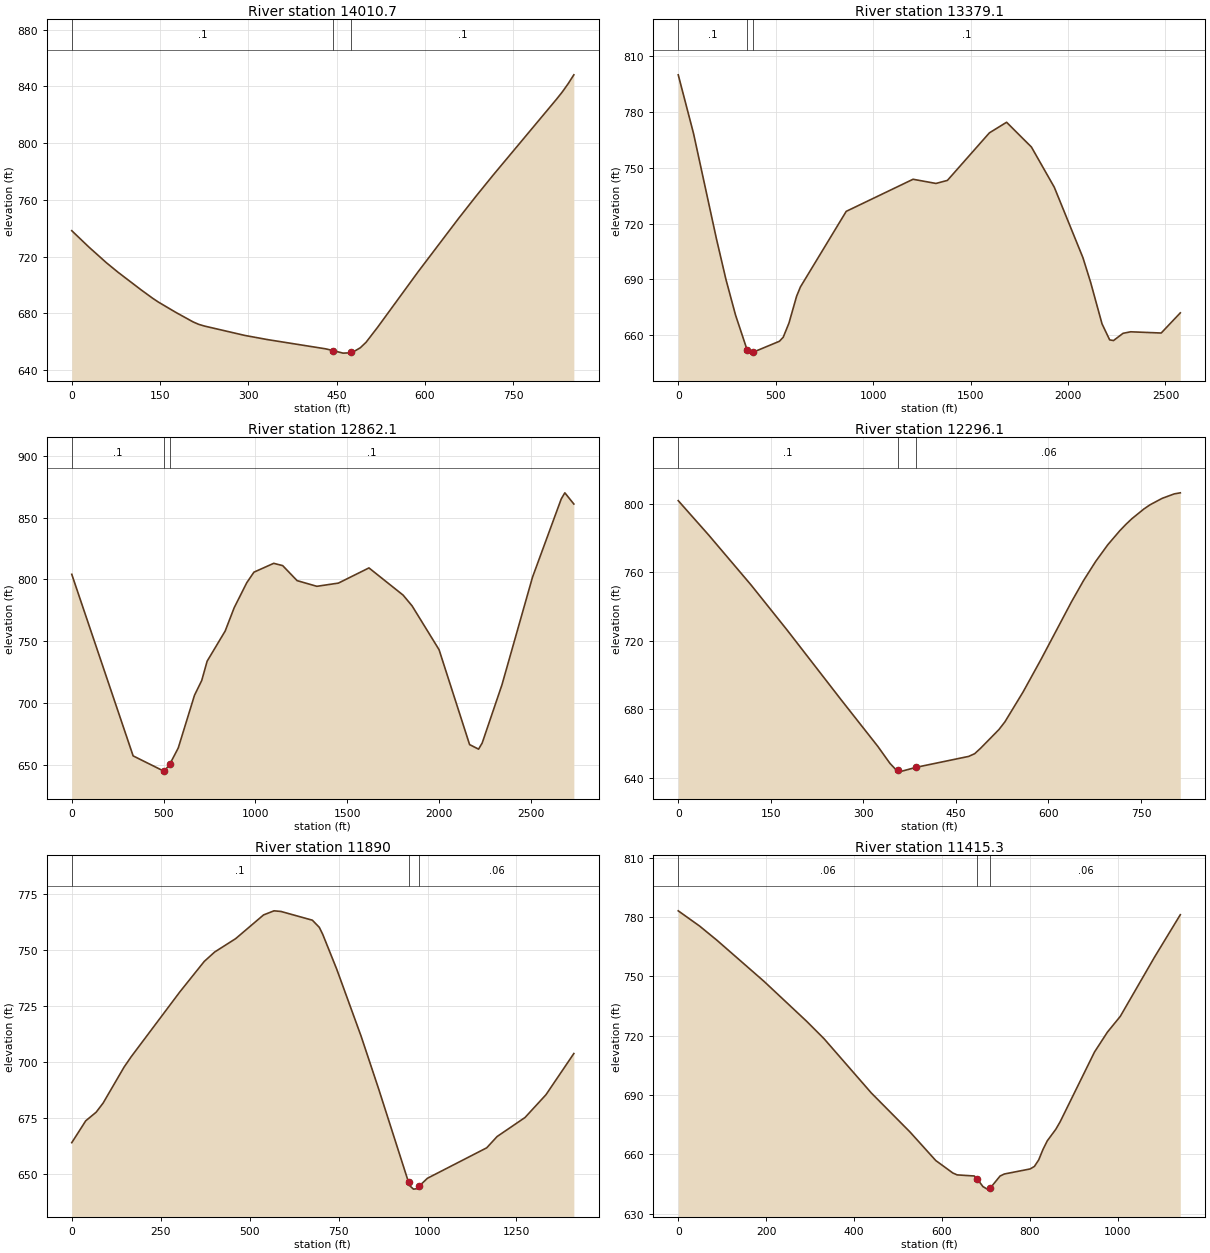
Type RM Length L Ch R = 1 ,14010.7 ,630.3,631.6,632.5
XS GIS Cut Line= 2
     1742782.523       587580.94     1743366.726      588202.218
#Sta/Elev= 30
       0   738.3    29.4  726.66    58.8  715.74    78.4  709.08   117.6  696.66
   137.2  690.74     147  688.02   176.4  680.81   205.8  674.07   215.6  672.29
   225.4  671.08   294.1  664.46   333.3  661.48   431.3  655.02   444.1  653.77
   460.7     652   470.5  652.17   474.7652.6928   480.3  653.39   490.1  655.78
   499.9  659.66   519.5  670.23   588.1  709.25   656.8  746.84   686.2  762.39
   715.6  777.44   823.4  831.02   833.2  836.13     843  841.86   852.8   848.2
#Mann= 3 , 0 , 0
       0      .1       0   444.1    .045       0   474.7      .1       0
Bank Sta=444.1,474.7
XS Rating Curve= 0 ,0
Exp/Cntr=0.3,0.1

Type RM Length L Ch R = 1 ,13379.1 ,469.4,517,544.9
XS GIS Cut Line= 3
     1742336.706      587953.309     1742719.592       588373.02
     1744500.064      589301.645
#Sta/Elev= 30
       0  800.04    78.4  768.52   195.9  711.85   244.9  689.87   293.8  670.83
   353.9  651.83   372.2  650.26   383.9650.7369   519.1  656.64   538.7  658.81
   568.1  666.42   607.3  680.86   626.9  685.87     862  726.56  1204.8  743.83
  1322.4  741.58  1381.2  743.22  1596.6  768.81  1684.8  774.51  1812.2  761.19
  1929.7  739.52  2076.6  701.62  2115.8  688.45  2174.6  665.99  2213.8  657.38
  2233.4  657.03  2282.3  660.92  2321.5  661.74  2478.2  661.08  2576.2  671.93
#Mann= 3 , 0 , 0
       0      .1       0   353.9    .045       0   383.9      .1       0
Bank Sta=353.9,383.9
XS Rating Curve= 0 ,0
Exp/Cntr=0.3,0.1

Type RM Length L Ch R = 1 ,12862.1 ,572,566,559.2
XS GIS Cut Line= 3
     1742092.097      588016.271     1742340.035      588814.702
     1743937.353      589843.426
#Sta/Elev= 30
       0  804.13   334.4  657.51   501.6  645.21   504.8  645.21   535.4651.1299
   580.3  663.93   668.8  706.48   708.2   718.4   737.7  734.01     836  758.34
     885  777.14   953.6  797.36   992.7  805.87  1100.5  813.01  1149.4  811.16
  1227.8  799.05  1335.5  794.45    1453  797.04  1619.5   809.3  1805.6  787.34
  1854.6  778.64  2001.5  743.28  2167.9  666.63  2216.9  662.96  2236.5  667.92
  2344.2  714.88  2510.7  801.79  2667.4  865.04    2687  869.94    2736   860.9
#Mann= 3 , 0 , 0
       0      .1       0   504.8    .045       0   535.4      .1       0
Bank Sta=504.8,535.4
XS Rating Curve= 0 ,0
Exp/Cntr=0.3,0.1

Type RM Length L Ch R = 1 ,12296.1 ,409.5,406.1,402.2
XS GIS Cut Line= 2
     1741580.026      588276.648     1741952.829      588999.871
#Sta/Elev= 30
       0  801.87      49  781.94   117.6  752.83   176.5  726.31   264.7   685.3
   323.5   658.4   343.1  648.51   352.9  644.81   355.9  644.56   362.7  643.99
   385.9646.2463   470.6  652.58   480.4  654.17   490.2  657.43   519.6  668.22
   529.4  672.77   558.8  690.19   588.2  709.41   637.2  742.78   656.8  755.24
   676.4  766.36     696  776.09   715.6  784.34   725.4  788.02   735.2  791.35
   754.8  797.07   764.6  799.47   784.2  803.22   803.8  805.82   813.6  806.44
#Mann= 3 , 0 , 0
       0      .1       0   355.9    .045       0   385.9     .06       0
Bank Sta=355.9,385.9
XS Rating Curve= 0 ,0
Exp/Cntr=0.3,0.1

Type RM Length L Ch R = 1 ,11890   ,485.5,474.7,463.9
XS GIS Cut Line= 2
      1740902.86      588026.559      1741667.05      589212.978
#Sta/Elev= 30
       0  663.85    39.2  673.62    68.6   677.5    88.2   681.6     147  697.67
   166.6  702.22   303.8  731.34   372.4  744.98   401.8   749.2   460.6  755.16
     539  765.78   568.4  767.62     588  767.34   676.2  763.43   695.8  760.22
   705.6  757.02   744.8  741.47   813.4  711.44   862.4  687.99   946.7  646.06
   950.6  644.49   960.4  643.06   970.2  643.23   976.7644.4504   999.6  647.91
  1166.2  661.54  1195.6  666.61    1274  675.12  1332.8   685.3  1411.2  703.75
#Mann= 3 , 0 , 0
       0      .1       0   946.7    .045       0   976.7     .06       0
Bank Sta=946.7,976.7
XS Rating Curve= 0 ,0
Exp/Cntr=0.3,0.1

Type RM Length L Ch R = 1 ,11415.3 ,563.5,580.7,598
XS GIS Cut Line= 2
     1740522.865      588672.715     1741388.276      589418.203
#Sta/Elev= 30
       0  783.18    48.8  775.44    87.9  768.32   195.2  747.48   292.9  727.12
   331.9  718.42   439.3     691   527.2  671.28   585.8  656.83   624.8   650.5
   634.6  649.55   673.6     649   680.2  647.48   693.2  643.64   702.9  642.35
   710.3643.0069   732.2  648.99     742  650.01   800.5  652.56   810.3  653.84
   820.1  657.16   829.8  662.45   839.6  666.81   859.1  672.68   868.9  676.46
     947  711.73   976.3  721.78  1005.6  729.76  1083.6  759.78  1142.2  781.21
#Mann= 3 , 0 , 0
       0     .06       0   680.2    .045       0   710.3     .06       0
Bank Sta=680.2,710.3
XS Rating Curve= 0 ,0
Exp/Cntr=0.3,0.1

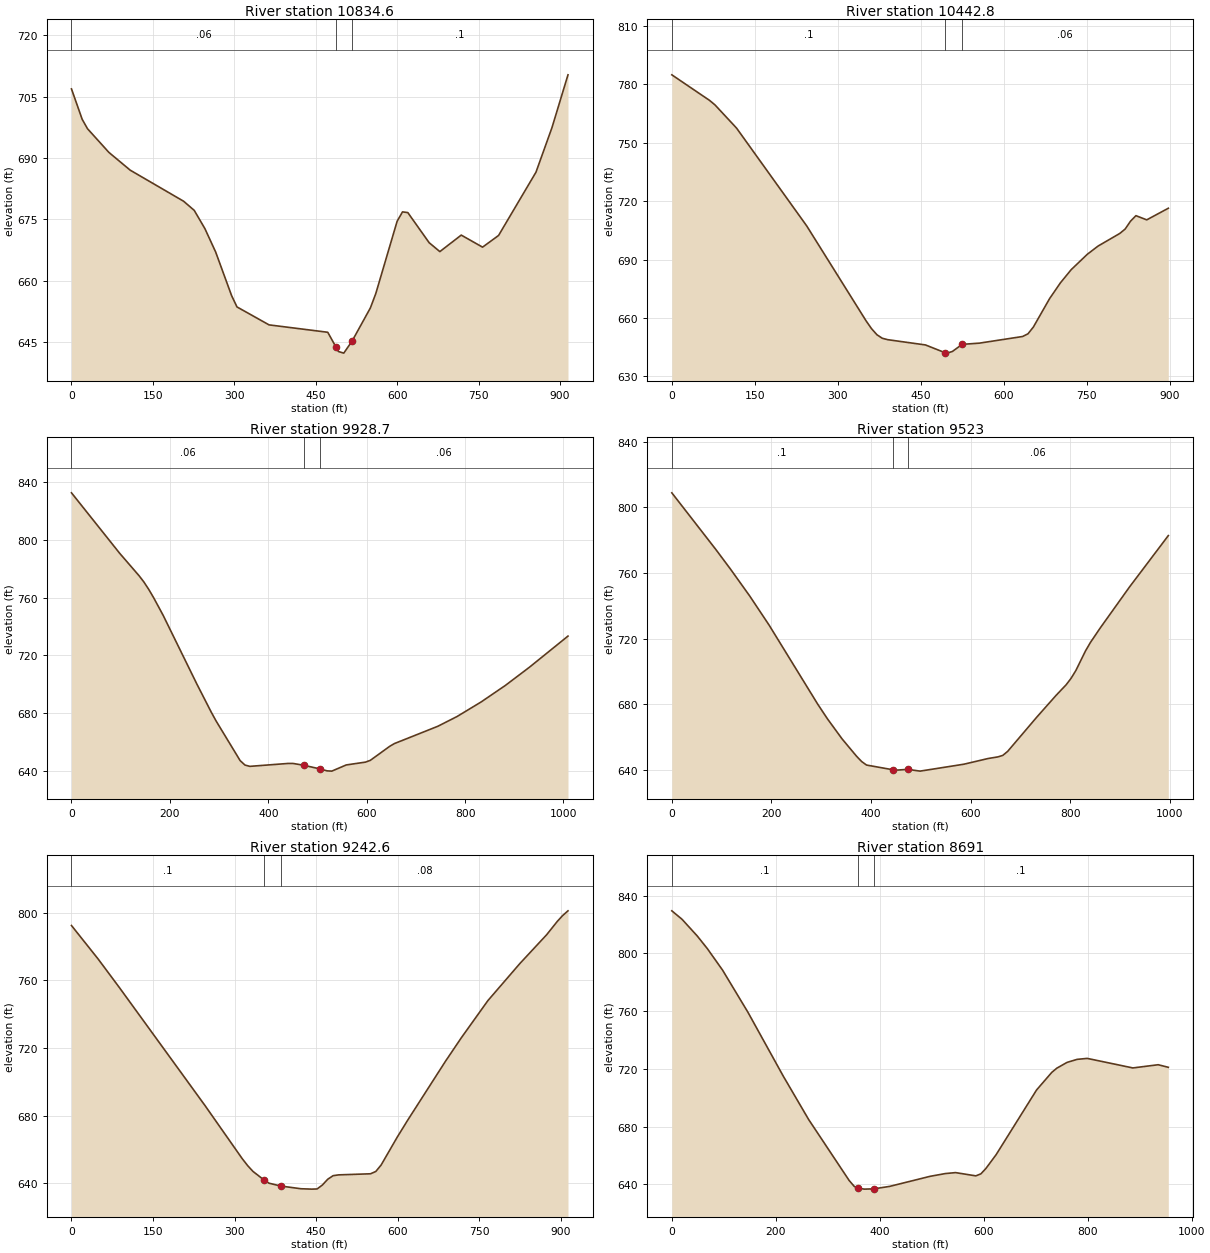
Type RM Length L Ch R = 1 ,10834.6 ,395,391.7,389.2
XS GIS Cut Line= 2
     1740434.775      589036.123     1740791.161      589878.647
#Sta/Elev= 30
       0  706.87    19.7  699.44    29.5  697.14    68.9  691.35   108.2     687
   206.6   679.4   226.2  677.16   245.9  672.68   265.6  666.99   295.1  656.29
   304.9  653.55     364  649.16   472.2  647.35   487.2  643.76   491.8  642.65
   501.7  642.25   517.2645.2422   550.8  653.33   560.7  656.83     600  674.51
   609.9   676.8   619.7  676.62     659  669.26   678.7  667.08   718.1  671.12
   757.4  668.17   786.9  671.03   855.8   686.5   885.3  697.41   914.8  710.32
#Mann= 3 , 0 , 0
       0     .06       0   487.2    .045       0   517.2      .1       0
Bank Sta=487.2,517.2
XS Rating Curve= 0 ,0
Exp/Cntr=0.3,0.1

Type RM Length L Ch R = 1 ,10442.8 ,543.8,514.1,485.9
XS GIS Cut Line= 2
       1740079.5      589126.075     1740428.945      589952.191
#Sta/Elev= 30
       0  784.93    68.2  771.79      78  769.47     117  757.54   243.8  707.26
     351  658.51   360.7  654.55   370.5   651.4   380.2  649.58     390  648.85
   458.2  646.15   493.7  642.15   497.2  641.94     507  642.81   524.4646.4321
   555.7  647.07   633.7  650.48   643.5  651.88   653.2  655.35   682.5  669.95
     702  678.03   721.5  684.82   750.7  692.74   770.2  696.97   809.2  703.41
     819  705.69   828.7  709.73   838.5  712.57     858  710.41     897  716.38
#Mann= 3 , 0 , 0
       0      .1       0   493.7    .045       0   524.4     .06       0
Bank Sta=493.7,524.4
XS Rating Curve= 0 ,0
Exp/Cntr=0.3,0.1

Type RM Length L Ch R = 1 ,9928.7  ,392.2,405.8,416.6
XS GIS Cut Line= 2
     1739501.554      589738.973     1740466.151      590035.528
#Sta/Elev= 30
       0  832.57      98  790.68   137.2  775.23     147  770.91   156.8  765.82
   166.6  760.17   186.2  747.83   254.7  700.26   284.1  680.69   293.9   674.6
   342.9   647.1   352.7  644.05   362.5  643.16   440.9  645.19   450.7  645.16
   472.1  643.91   504.5641.4504   519.3  640.06   529.1  639.86   558.5  644.14
   597.6   646.1   607.4  647.32   646.6  656.99   656.4  658.94   744.6  670.91
   783.8  677.69   832.8  687.79   881.8  699.17   930.8  711.79  1009.2  733.36
#Mann= 3 , 0 , 0
       0     .06       0   472.1    .045       0   504.5     .06       0
Bank Sta=472.1,504.5
XS Rating Curve= 0 ,0
Exp/Cntr=0.3,0.1

Type RM Length L Ch R = 1 ,9523    ,272.4,280.4,288.3
XS GIS Cut Line= 2
      1739489.44      589924.278     1740238.431      590581.964
#Sta/Elev= 30
       0  808.93      88  774.55   117.3  762.64   156.4  746.06   195.4  728.27
   293.2     680   312.7  671.09     342   658.9   371.3  648.26   381.1  645.18
   390.9  643.03   443.1   640.2   449.5   639.9   473.3640.4014   498.4  639.33
   586.3  643.54   635.2  647.03   654.7  648.01   664.5  648.92   674.3  651.38
   732.9   672.3     772  685.68   791.6  691.93   801.3  695.78   811.1   700.6
   830.6  712.63   840.4  717.74     860  726.53   918.6  751.44   996.8  782.87
#Mann= 3 , 0 , 0
       0      .1       0   443.1    .045       0   473.3     .06       0
Bank Sta=443.1,473.3
XS Rating Curve= 0 ,0
Exp/Cntr=0.3,0.1

Type RM Length L Ch R = 1 ,9242.6  ,547.9,551.6,554.4
XS GIS Cut Line= 2
      1739379.32       590083.81     1739926.737      590815.175
#Sta/Elev= 30
       0  792.46    49.1  772.64    88.4  755.66   245.6  686.04   314.3  654.54
   324.2  650.47     334  647.05   354.8  641.87   363.4  640.11   384.9638.4292
   422.4  636.82     442   636.6   451.9   636.7   461.7  639.06   471.5  642.45
   481.3  644.54   491.2  645.02   550.1  645.67   559.9  647.03   569.7  650.86
   599.2  667.26   618.8  677.48   687.6  711.96   717.1  726.02   766.2  748.09
   825.1  770.03   874.2     787   893.9  794.93   903.7  798.36   913.5  801.15
#Mann= 3 , 0 , 0
       0      .1       0   354.8    .045       0   384.9     .08       0
Bank Sta=354.8,384.9
XS Rating Curve= 0 ,0
Exp/Cntr=0.3,0.1

Type RM Length L Ch R = 1 ,8691    ,413.9,406.7,400.6
XS GIS Cut Line= 2
     1738912.256      590306.172     1739449.455       591095.89
#Sta/Elev= 30
       0   829.5    19.5  823.69    48.7  812.16    68.2  803.37    97.5  788.46
   146.2  759.34   214.4  714.91   263.1  684.92   341.1  642.61   350.9  638.51
   357.5  637.29   370.4   636.6   388.6636.7927   419.1   638.5     497  645.49
   526.3  647.39   545.8  648.05   584.8  645.79   594.5  647.18   604.2  650.92
   623.8  660.45   701.7  705.35     731  717.55   740.7  720.46   760.2  724.43
   779.7  726.55   799.2  727.21   886.9   720.6   935.6  722.82   955.1  721.04
#Mann= 3 , 0 , 0
       0      .1       0   357.5    .045       0   388.6      .1       0
Bank Sta=357.5,388.6
XS Rating Curve= 0 ,0
Exp/Cntr=0.3,0.1

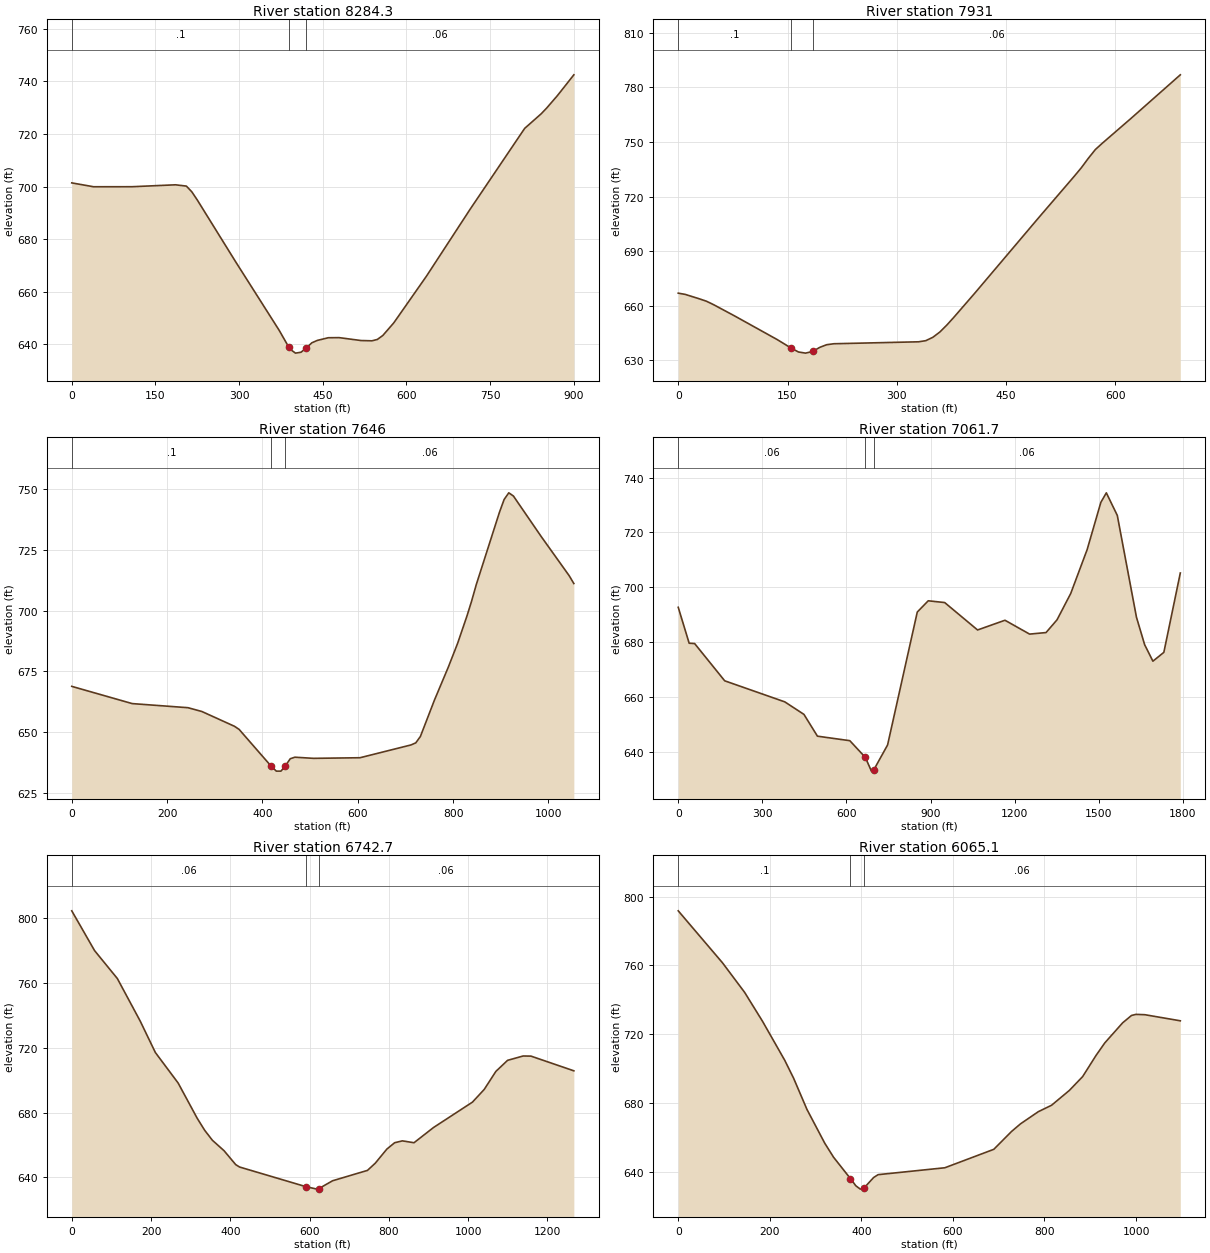
Type RM Length L Ch R = 1 ,8284.3  ,356.2,353.3,349.5
XS GIS Cut Line= 2
     1738586.603      590612.144     1739216.989      591254.761
#Sta/Elev= 30
       0  701.41    39.1  699.94   107.6  699.95   185.9  700.68   205.5  700.19
   215.3     698     225  694.93   293.5  671.52   371.8  645.38   389.3  638.88
   391.4  638.16   401.2  636.68     411  637.02   420.3638.6115   430.5  640.61
   440.3  641.52   459.9  642.53   479.4  642.57   518.6  641.47   538.2  641.36
   547.9  641.88   557.7  643.39   577.3  648.17     636  665.96   714.3  691.41
   812.1  722.15   841.5  727.65   851.3  729.82   870.8  734.61   900.2   742.5
#Mann= 3 , 0 , 0
       0      .1       0   389.3    .045       0   420.3     .06       0
Bank Sta=389.3,420.3
XS Rating Curve= 0 ,0
Exp/Cntr=0.3,0.1

Type RM Length L Ch R = 1 ,7931    ,246.8,285,323
XS GIS Cut Line= 2
     1738534.616      591051.669     1739051.682      591507.366
#Sta/Elev= 30
       0  666.95     9.7  666.25    29.1  663.82    38.8   662.5    48.5  660.63
    77.7  654.37   135.9  641.44   155.4  636.68     165  634.65   174.7  634.01
   184.4  634.91   185.6635.1855   194.2  637.16   203.8  638.63   213.6  639.16
     330  640.23   339.8  640.85   349.5   642.7   359.2  645.63   368.9   649.5
   378.6   653.8   407.7  667.23   495.1  708.53   543.6  731.12   553.3  735.78
     563  741.02   572.7  745.86   582.4  749.37   621.3  762.83   689.2  786.84
#Mann= 3 , 0 , 0
       0      .1       0   155.4    .045       0   185.6     .06       0
Bank Sta=155.4,185.6
XS Rating Curve= 0 ,0
Exp/Cntr=0.3,0.1

Type RM Length L Ch R = 1 ,7646    ,525,584.3,643.4
XS GIS Cut Line= 2
     1738482.401      590791.994     1738313.717      591831.683
#Sta/Elev= 30
       0  668.79   126.8  661.68   243.8  659.99   273.1  658.41   341.3  652.33
   351.1  651.04   417.7  636.02   429.1  633.84   438.9  633.84   447.8635.9412
   458.4  638.95   468.1  639.58   507.1  639.11   604.7  639.36   711.9  644.65
   721.7   645.5   731.4  648.13   760.7  663.05     790  676.74   809.5  686.53
     829  697.76   838.7  703.86   848.5  710.66   897.2  740.54     907  745.82
   916.8  748.58   926.5  747.27     985  730.51  1043.5  714.42  1053.3  711.18
#Mann= 3 , 0 , 0
       0      .1       0   417.7    .045       0   447.8     .06       0
Bank Sta=417.7,447.8
XS Rating Curve= 0 ,0
Exp/Cntr=0.3,0.1

Type RM Length L Ch R = 1 ,7061.7  ,336.9,319,288.5
XS GIS Cut Line= 4
     1738491.487      590448.037     1738406.549      590888.176
     1738004.483      590846.135     1738073.497      591781.544
#Sta/Elev= 30
       0  692.69      39  679.57    58.5  679.45   165.7  665.86     380  658.17
   448.3   653.6   496.4  645.65   611.9     644   667.3   637.9   688.9  632.89
   697.3633.3362   746.6  642.44   852.5  690.96   891.6  695.06   950.2  694.42
  1067.5  684.41  1165.2  687.96  1253.1   682.9  1311.7  683.47  1350.8  688.11
  1399.7  697.73  1458.3  713.76  1507.1  730.98  1526.7  734.47  1565.8  726.22
  1634.1  689.08  1663.4  679.01  1692.8  673.02  1731.8  676.24  1790.5  705.21
#Mann= 3 , 0 , 0
       0     .06       0   667.3    .045       0   697.3     .06       0
Bank Sta=667.3,697.3
XS Rating Curve= 0 ,0
Exp/Cntr=0.3,0.1

Type RM Length L Ch R = 1 ,6742.7  ,744.2,677.6,622.8
XS GIS Cut Line= 4
     1738502.441      590122.217     1738442.591      590462.106
     1737956.492      590642.096     1737986.476      591044.332
#Sta/Elev= 30
       0  804.74    57.5  780.17     115   762.9   172.6  736.64   210.9  717.19
   268.4  698.32   316.4  676.57   335.5  669.07   354.9  662.92   384.2   656.5
   413.6   647.9   423.4  646.41   591.6  634.21     619  632.75   622.6632.9578
   658.1  637.92   746.1  644.33   765.7  648.76     795  657.48   814.6  661.42
   834.1  662.58   863.5  661.42   912.7  670.82    1011  686.52  1040.6  694.34
  1070.1  705.52  1099.6  712.34  1138.9  715.03  1158.6  714.95  1266.8  705.87
#Mann= 3 , 0 , 0
       0     .06       0   591.6    .045       0   622.6     .06       0
Bank Sta=591.6,622.6
XS Rating Curve= 0 ,0
Exp/Cntr=0.3,0.1

Type RM Length L Ch R = 1 ,6065.1  ,710.4,683.3,655.9
XS GIS Cut Line= 4
     1737615.367       590037.13     1737608.283      590182.017
     1737931.427      590736.037     1737953.539      591045.549
#Sta/Elev= 30
       0  791.71    96.7  761.46   145.1  744.24   183.9  727.54   232.5  704.82
     252  694.32   281.1   676.2     320  656.52   339.4   648.3   376.2  635.89
     388  631.71   397.7  629.78   406.4 630.623   426.9  636.56   436.6   638.2
   582.4  642.21   689.3  652.94   728.1  663.34   747.6  667.76   786.4  674.82
   815.5  678.59   854.3   687.2   883.4  695.26   912.5  707.52   931.9  714.91
   970.7  726.53   990.1  730.83   999.8  731.46  1019.2  731.27  1096.7  727.72
#Mann= 3 , 0 , 0
       0      .1       0   376.2    .045       0   406.4     .06       0
Bank Sta=376.2,406.4
XS Rating Curve= 0 ,0
Exp/Cntr=0.3,0.1