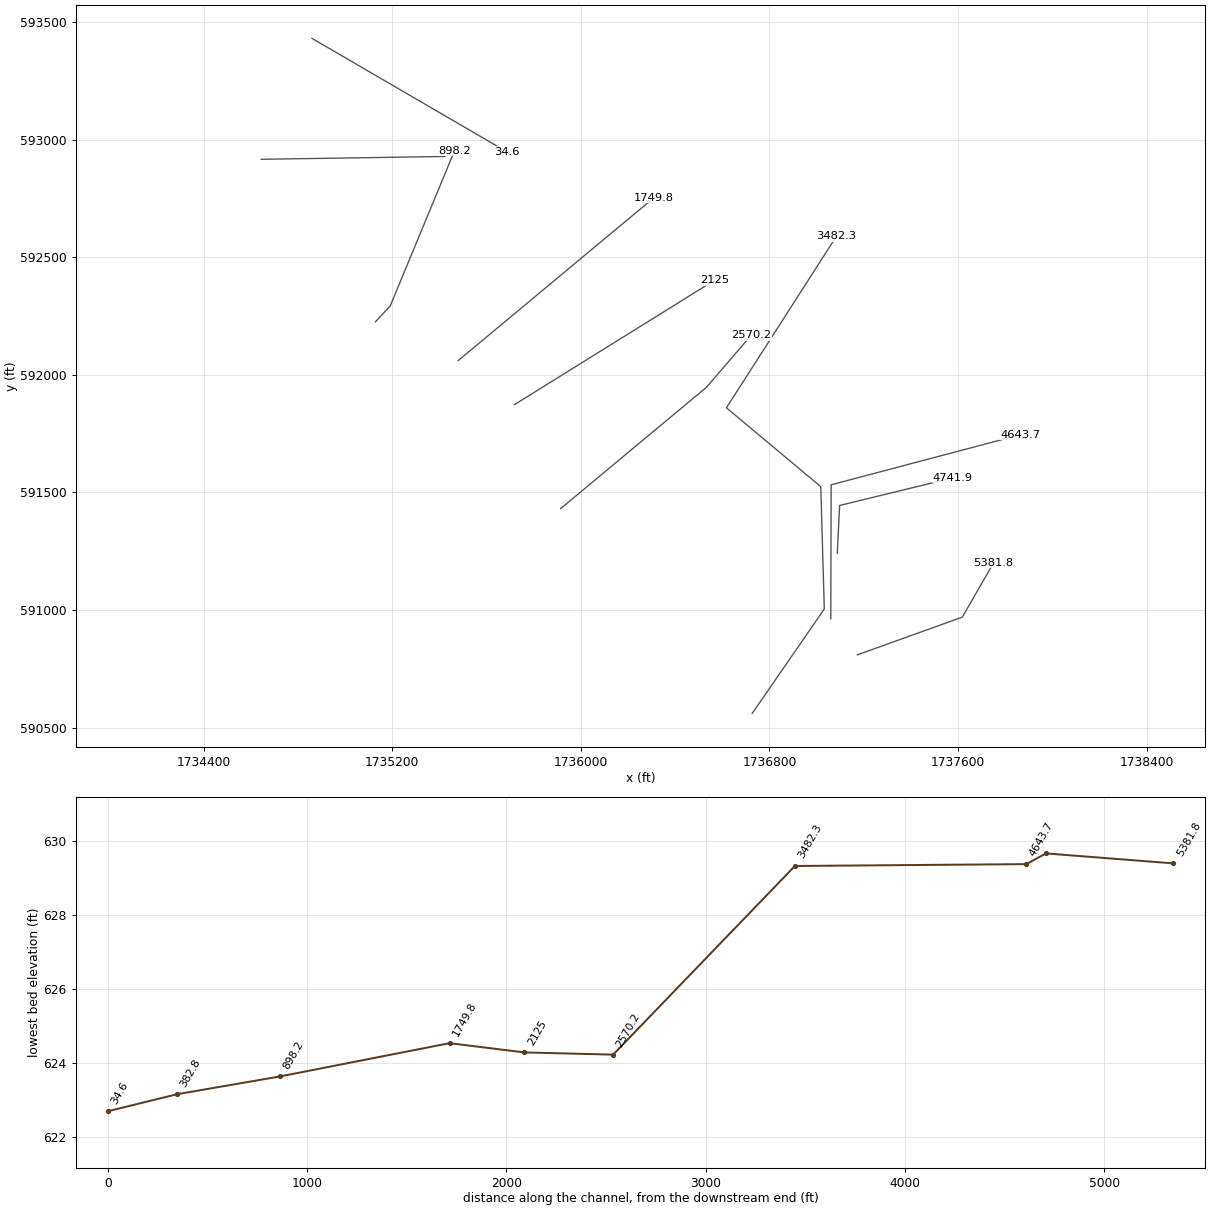
HEC-RAS study CherryFk.prj: CherryFk

--- CherryFk.g01 (geometry) --- (continued)

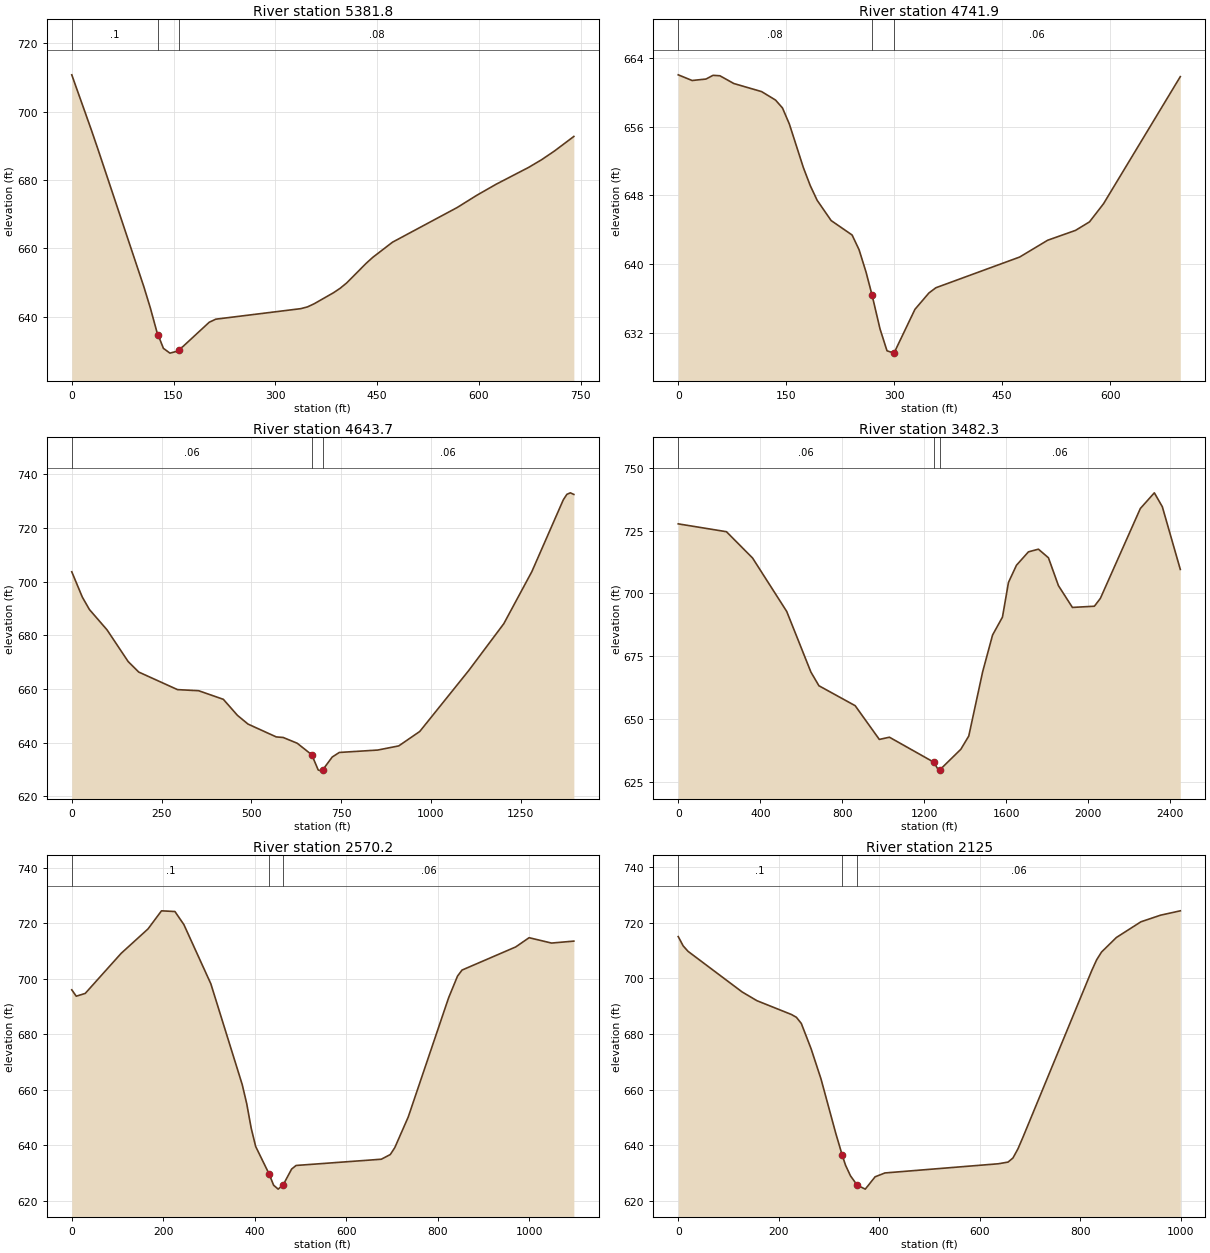
Type RM Length L Ch R = 1 ,5381.8  ,643.3,639.8,634.8
XS GIS Cut Line= 3
     1737173.031      590809.573     1737617.956      590969.589
     1737751.221      591201.284
#Sta/Elev= 30
       0  710.73      29  694.55    38.6  688.98   106.1   648.9   115.8  642.62
   125.4  635.65   127.4  634.65   135.1  630.79   144.7   629.4   154.4   629.9
   157.9630.4286     164  631.35   202.6  638.42   212.3  639.32   337.7   642.4
   347.4  642.91     357  643.79     386  647.07   395.6  648.35   405.3  649.92
   434.2  655.69   443.9  657.42   472.8  661.82   568.3  671.97   596.9  675.51
   625.6  678.76   673.3  683.66   692.4   685.9   711.5  688.46   740.1  692.72
#Mann= 3 , 0 , 0
       0      .1       0   127.4    .045       0   157.9     .08       0
Bank Sta=127.4,157.9
XS Rating Curve= 0 ,0
Exp/Cntr=0.3,0.1

Type RM Length L Ch R = 1 ,4741.9  ,97.7,98.2,99
XS GIS Cut Line= 3
     1737087.897      591242.046     1737097.763      591444.511
     1737578.321      591561.764
#Sta/Elev= 30
       0  662.02    19.3  661.36    38.6  661.53    48.3  661.96    57.9  661.91
    77.2  661.01   115.8  660.07   135.1  659.09   144.8  658.17   154.4  656.29
   173.8  651.24   183.4  649.14     193  647.43   212.4  645.08   241.5   643.4
   251.2  641.69   260.9  639.08   269.3  636.39   280.3  632.48     290  629.94
   299.7  629.67   328.8  634.76   348.2  636.66   357.9  637.27   474.3  640.84
   513.1  642.79   551.9  643.94   571.3  644.93   590.7  647.03   697.4  661.81
#Mann= 3 , 0 , 0
       0     .08       0   269.3    .045       0   299.7     .06       0
Bank Sta=269.3,299.7
XS Rating Curve= 0 ,0
Exp/Cntr=0.3,0.1

Type RM Length L Ch R = 1 ,4643.7  ,1061.4,1161.4,1245.5
XS GIS Cut Line= 3
     1737060.232      590962.977     1737061.831        591532.4
     1737863.045      591744.696
#Sta/Elev= 30
       0  703.71    29.4  694.27    49.1  689.65    98.2  682.06   157.1  670.23
   186.5  666.32   294.5  659.77   353.4  659.36   422.2  656.15   461.4  650.18
   490.9  646.92   569.4  642.14   588.9  641.92   627.9  639.78   668.4  635.48
   686.4   629.8   696.2  629.38   698.5629.7783   725.4  634.64     745  636.34
   852.2  637.24   910.7  638.79   969.2  644.17  1105.8  666.93  1203.3  684.37
  1281.3  703.76    1369  730.56  1378.8  732.57  1388.5  733.15  1398.3  732.55
#Mann= 3 , 0 , 0
       0     .06       0   668.4    .045       0   698.5     .06       0
Bank Sta=668.4,698.5
XS Rating Curve= 0 ,0
Exp/Cntr=0.3,0.1

Type RM Length L Ch R = 1 ,3482.3  ,973,912.1,851.1
XS GIS Cut Line= 5
     1736727.033      590560.612     1737032.774      591004.329
     1737017.724      591524.536     1736617.535      591859.637
     1737084.967      592590.145
#Sta/Elev= 30
       0  727.65   235.1  724.53   362.5  714.07   529.1  692.82   646.9  668.74
   686.1  663.28   862.9  655.35   980.7  641.93  1029.8  642.82  1246.1  632.89
  1271.9  629.33  1277.3629.9647  1378.2  638.02  1416.9   643.3  1484.6  668.84
  1532.9  683.44  1581.2  690.58  1610.5  704.36  1649.4  711.19  1707.9  716.52
  1756.6  717.58  1805.4  714.17  1854.1  703.09  1922.3  694.42  2029.5   694.9
  2058.7  698.02  2253.6  733.76  2321.8  739.99  2360.8  734.46  2448.5  709.53
#Mann= 3 , 0 , 0
       0     .06       0  1246.1    .045       0  1277.3     .06       0
Bank Sta=1246.1,1277.3
XS Rating Curve= 0 ,0
Exp/Cntr=0.3,0.1

Type RM Length L Ch R = 1 ,2570.2  ,453,445.2,436.3
XS GIS Cut Line= 3
     1735914.897      591431.583     1736532.418      591946.533
     1736723.659      592169.032
#Sta/Elev= 30
       0  696.02     9.8  693.72    29.4  694.72   107.9  709.15   166.7  717.96
   196.1  724.47   225.5  724.22   245.1   719.5     304  698.18   372.6  661.87
   382.4     655   392.2  646.17     402  639.58   431.2  629.73   441.2  625.64
   451.1  624.23   462.4625.8598   480.5  631.45   490.3  632.75   676.6     635
   696.2  636.69     706  639.16   735.4   650.2   823.6  693.11   843.2  700.97
     853  703.13   970.3  711.46   999.6  714.79  1048.6  712.86  1097.4  713.56
#Mann= 3 , 0 , 0
       0      .1       0   431.2    .045       0   462.4     .06       0
Bank Sta=431.2,462.4
XS Rating Curve= 0 ,0
Exp/Cntr=0.3,0.1

Type RM Length L Ch R = 1 ,2125    ,369.2,375.2,380.8
XS GIS Cut Line= 2
     1735718.517      591873.211     1736566.532      592401.488
#Sta/Elev= 30
       0  714.98     9.8  711.65    19.6  709.67   127.3  695.08   156.7  691.95
   225.3     687   235.1     686   244.9   683.8   264.5  674.64   284.1  663.86
   313.4  644.38   326.2  636.56     333  632.84   342.8  629.05   356.2   625.7
   372.2  624.29   391.8  628.72   411.4   630.1   636.7  633.39   656.3     634
   666.1  635.48   675.9  638.72   685.7  642.81   822.8  702.75   832.6  706.64
   842.4  709.44   871.8  714.64   920.7  720.29   959.9  722.67   999.1  724.23
#Mann= 3 , 0 , 0
       0      .1       0   326.2    .045       0   356.2     .06       0
Bank Sta=326.2,356.2
XS Rating Curve= 0 ,0
Exp/Cntr=0.3,0.1

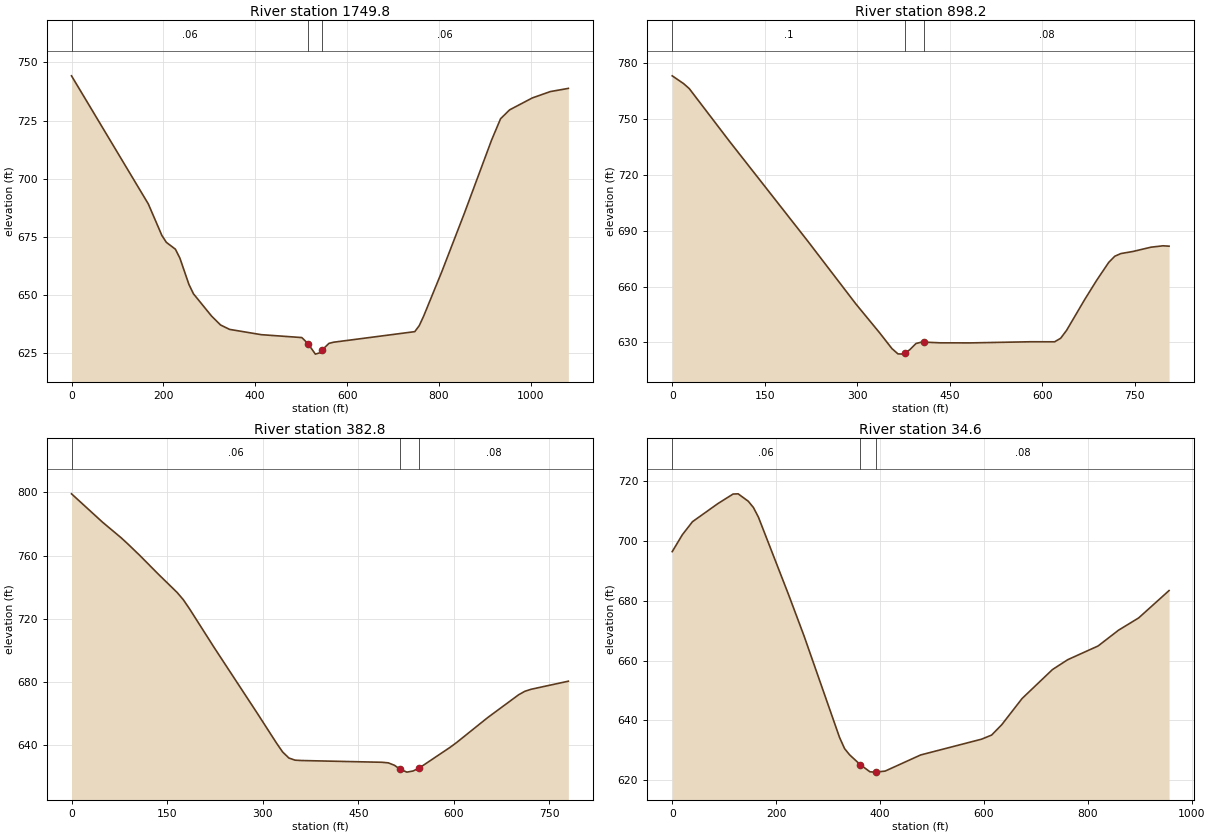
Type RM Length L Ch R = 1 ,1749.8  ,829.6,851.6,872.1
XS GIS Cut Line= 2
     1735479.977      592060.636     1736310.766       592753.43
#Sta/Elev= 30
       0  744.24   167.2  689.15   196.7  675.61   206.5  672.62   226.2  669.67
     236  665.83   255.7   654.5   265.5   650.5   304.9  640.92   324.5  637.08
   344.2  635.18     413  632.91   501.5  631.66     515  629.02     531  624.54
   540.9  625.13     545626.1801   560.5  629.16   570.4  629.66   747.4  634.21
   757.2   636.8   767.1  641.06   806.4  660.07   855.6  685.24   914.6  716.59
   934.2  725.78   953.9   729.6  1003.1  734.71  1042.4  737.46  1081.8  738.84
#Mann= 3 , 0 , 0
       0     .06       0     515    .045       0     545     .06       0
Bank Sta=515,545
XS Rating Curve= 0 ,0
Exp/Cntr=0.3,0.1

Type RM Length L Ch R = 1 ,898.2   ,560.1,515.4,470
XS GIS Cut Line= 3
     1735128.927      592225.316     1735191.726       592293.21
     1735464.302      592952.602
#Sta/Elev= 30
       0  773.32    18.5  769.12    27.8  766.39    92.5  738.27   219.6  684.55
   297.7  650.72   336.8  634.96   356.4  626.63   366.2  623.77   375.9  623.64
   377.6  624.07   385.7  626.12   395.5  629.36   405.2  630.16   408.4630.1077
   434.6  629.72   483.4  629.68   581.2  630.29   620.3  630.27   630.1  632.17
   639.8  636.46   669.2  653.04   688.7  663.42   708.2  673.01     718   676.3
   727.8  677.73   747.4  678.85   776.7  681.16   796.2   681.9     806   681.7
#Mann= 3 , 0 , 0
       0      .1       0   377.6    .045       0   408.4     .08       0
Bank Sta=377.6,408.4
XS Rating Curve= 0 ,0
Exp/Cntr=0.3,0.1

Type RM Length L Ch R = 1 ,382.8   ,370.5,348.2,326.2
XS GIS Cut Line= 2
     1734644.016      592916.216     1735423.514      592928.199
#Sta/Elev= 30
       0  799.14    48.7   781.2      78  771.32    87.7  767.72   107.2  760.17
   136.4  748.28   165.7  736.78   175.4   732.2   185.2  726.41   224.1  701.79
   292.4  659.84   321.6  641.56   331.3  635.89   341.1  632.09   350.8  630.72
   360.6   630.5   487.2  629.39     497  629.03   506.7  627.49   515.1  625.13
   526.2  623.16     536  623.88   545.7  625.78   594.4  638.94   604.2  641.86
   652.9  657.61   701.6  672.08   711.4  674.28   721.1  675.55   779.6  680.66
#Mann= 3 , 0 , 0
       0     .06       0   515.1    .045       0   545.7     .08       0
Bank Sta=515.1,545.7
XS Rating Curve= 0 ,0
Exp/Cntr=0.3,0.1

Type RM Length L Ch R = 1 ,34.6    ,39.7,34.6,29.5
XS GIS Cut Line= 2
     1734859.353      593430.442     1735685.572      592948.486
#Sta/Elev= 30
       0  696.49    19.5  702.14      39   706.5    87.8  712.55   117.1  715.75
   126.9  715.83   146.4  713.35   156.2  711.28   165.9  708.05   224.5  681.86
   253.8  668.27   322.1  634.32   331.8  630.57   341.6  628.47     362  625.21
   380.6  622.81   390.4   622.7   392.1622.7052   409.9  623.05   478.3  628.45
   595.4  633.72   614.9   635.1   634.4  638.57   673.5  647.33     732  657.02
   761.3  660.32   819.9  664.92   858.9  670.16     898  674.31   956.5  683.46
#Mann= 3 , 0 , 0
       0     .06       0     362    .045       0   392.1     .08       0
Bank Sta=362,392.1
XS Rating Curve= 0 ,0
Exp/Cntr=0.3,0.1

Chan Stop Cuts=-1
Use User Specified Reach Order=0
Composite Channel Slope=5